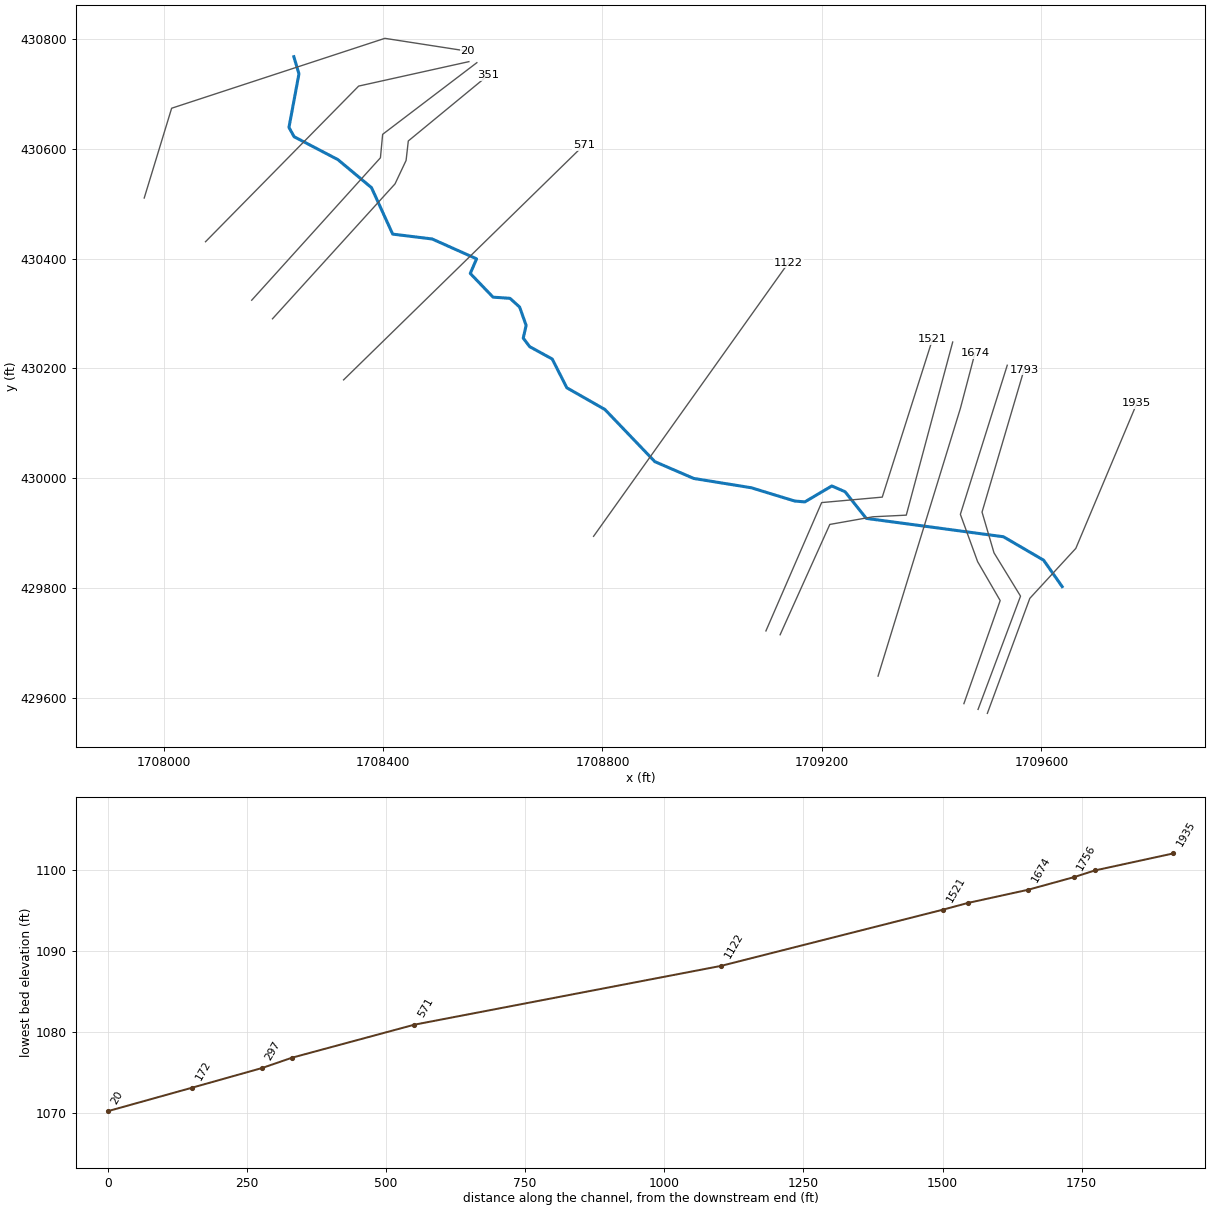
--- SANTEERN.prj (project) ---

Proj Title=SANTEERN
Current Plan=p01
Default Exp/Contr=0.3,0.1
English Units
Geom File=g01
Flow File=f01
Plan File=p01
Y Axis Title=Elevation
X Axis Title(PF)=Main Channel Distance
X Axis Title(XS)=Station
BEGIN DESCRIPTION:
---------- MODELED AS PART OF WVEMD CTP PROGRAM, 2023----------
Stream Name: Santee Run
Flood Zone:  AFH
Wetzel County, WV
HEC-RAS Version: RAS 6.3
Vertical Datum: NAVD88
Projection: NAD 1983 StatePlane West Virginia S FIPS 4702 (US Feet)
Terrain: 1-meter West Virginia FEMA R3 South Central (collected 2018-2020)
Land Use: 2019 NLCD
Hydrologic Method:
WV SIR2010-5033 regression equations
Additional Model Notes:
None
END DESCRIPTION:
DSS Export Rating Curves= 0
DSS Export Rating Curve Sorted= 0
DSS Export Volume Flow Curves= 0
DXF OffsetX= 0
DXF OffsetY= 0
DXF ScaleX= 1
DXF ScaleY= 10

--- SANTEERN.p01 (plan) ---

Plan Title=Floodplain
Program Version=6.30
Short Identifier=Floodplain
Geom File=g01
Flow File=f01
Subcritical Flow
K Sum by GR= 0
Std Step Tol= 0.01
Critical Tol= 0.01
Num of Std Step Trials= 20
Max Error Tol= 0.3
Flow Tol Ratio= 0.001
Split Flow NTrial= 30
Split Flow Tol= 0.02
Split Flow Ratio= 0.02
Log Output Level= 0
Friction Slope Method= 1
Unsteady Friction Slope Method= 2
Unsteady Bridges Friction Slope Method= 1
Parabolic Critical Depth
Global Vel Dist= 0 , 0 , 0
Global Log Level= 0
CheckData=True
Encroach Param=-1 ,0,0, 0
Computation Interval=1MIN
Output Interval=1HOUR
Instantaneous Interval=1HOUR
Mapping Interval=1HOUR
Computation Time Step Use Courant=        0
Computation Time Step Use Time Series=    0
Computation Time Step Count To Double=0
Computation Time Step Max Doubling=0
Computation Time Step Max Halving=0
Computation Time Step Residence Courant=0
Run HTab= 0
Run UNet= 0
Run Sediment= 0
Run PostProcess= 0
Run WQNet= 0
Run RASMapper= 0
UNET Theta= 1
UNET Theta Warmup= 1
UNET ZTol= 0.02
UNET ZSATol= 0.02
UNET MxIter= 20
UNET Max Iter WO Improvement= 0
UNET MaxInSteps= 0
UNET DtIC= 0
UNET DtMin= 0
UNET MaxCRTS= 20
UNET WFStab= 2
UNET SFStab= 1
UNET WFX= 1
UNET SFX= 1
UNET Gravity=32.17405
UNET 1D Methodology=Finite Difference
UNET DSS MLevel= 4
UNET Pardiso=0
UNET DZMax Abort= 100
UNET Use Existing IB Tables=-1
UNET Froude Reduction=False
UNET Froude Limit= 0.8
UNET Froude Power= 4
UNET D1 Cores= 0
UNET WindReference=Eulerian
UNET WindDragFormulation=Hsu (1988)
UNET D2 Coriolis=0
UNET D2 Cores= 0
UNET D2 Theta= 1
UNET D2 Theta Warmup= 1
UNET D2 Z Tol= 0.01
UNET D2 Volume Tol= 0.01
UNET D2 Max Iterations= 20
UNET D2 Equation= 0
UNET D2 RampUpFraction=0.1
UNET D2 TimeSlices= 1
UNET D2 Turbulence Formulation=None
UNET D2 Eddy Viscosity=0.3
UNET D2 Transverse Eddy Viscosity=0.1
UNET D2 Smagorinsky Mixing=0.05
UNET D2 BCVolumeCheck=0
UNET D2 Cores=0
UNET D2 SolverType=PARDISO (Direct)
UNET D2 Minimum Iterations= 3
UNET D2 Maximum Iterations= 30
UNET D2 Restart Number= 10
UNET D2 Relaxation Coeff=1.3
UNET D2 SOR Precondition Iterations= 10
UNET D2 ILUT Maximum Fill= 8
UNET D2 ILUT Tolerance=1E-08
UNET D2 Convergence Tolerance=0.00001
UNET D1D2 MaxIter= 0
UNET D1D2 ZTol=0.01
UNET D1D2 QTol=0.1
UNET D1D2 MinQTol=1
Write IC File= 0
Write IC File at Fixed DateTime=0
Write IC File at Sim End=0
Echo Input=False
Echo Parameters=False
Echo Output=False
Write Detailed= 0
HDF Write Warmup=0
HDF Write Time Slices=0
HDF Flush=0
HDF Compression= 1
HDF Chunk Size= 1
HDF Spatial Parts= 1
HDF Use Max Rows=0
HDF Fixed Rows= 1
Calibration Method= 0
Calibration Iterations= 20
Calibration Max Change=0.05
Calibration Tolerance=0.2
Calibration Maximum=1.5
Calibration Minimum=0.5
Calibration Optimization Method= 1
WQ AD Non Conservative
WQ ULTIMATE=-1
WQ Max Comp Step=1HOUR
WQ Output Interval=15MIN
WQ Output Selected Increments= 0
WQ Output face flow=0
WQ Output face velocity=0
WQ Output face area=0
WQ Output face dispersion=0
WQ Output cell volume=0
WQ Output cell surface area=0
WQ Output cell continuity=0
WQ Output cumulative cell continuity=0
WQ Output face conc=0
WQ Output face dconc_dx=0
WQ Output face courant=0
WQ Output face peclet=0
WQ Output face adv mass=0
WQ Output face disp mass=0
WQ Output cell mass=0
WQ Output cell source sink temp=0
WQ Output nsm pathways=0
WQ Output nsm derived pathways=0
WQ Create Restart=0
WQ Fixed Restart=0
WQ System Summary=0
WQ Write To DSS=0
Sorting and Armoring Iterations= 10
XS Update Threshold= 0.02
Bed Roughness Predictor= 0
Hydraulics Update Threshold= 0.02
Energy Slope Method= 1
Volume Change Method= 1
Sediment Retention Method= 0
Sediment TS Multiplier= 1
Warm Up Method= 0
XS Weighting Method= 0
Number of US Weighted Cross Sections= 1
Number of DS Weighted Cross Sections= 1
Upstream XS Weight=0
Main XS Weight=1
Downstream XS Weight=0
Number of DS XS's Weighted with US Boundary= 1
Upstream Boundary Weight= 1
Weight of XSs Associated with US Boundary= 0
Number of US XS's Weighted with DS Boundary= 1
Downstream Boundary Weight= 0.5
Weight of XSs Associated with DS Boundary= 0.5
Percentile Method= 0
Sediment Output Level= 3
Mass or Volume Output= 0
Output Increment Type= 1
Profile and TS Output Increment= 1
Transport Output Increment 1
XS Output Flag= 0
XS Output Increment= 10
Read HDF5 Sediment Hotstart= 0
Sediment Hotstart Type= 0
Write Gradation File= 0
Read Gradation Hotstart= 0
Write HDF5 File= 1
Write Binary Output= 1
Write DSS Sediment File= 0
DSS Sediment Output Type= 1
SV Curve= 0
Specific Gage Flag= 0
Subcell Erosion Methods= 0
Subcell Deposition Methods= 0
Advection Scheme= 1
Matrix Solver= 0
Implicit Weighting Factor= 1
Maximum Outer Loop Convergence Iterations= 5
Convergence Maximum Absolute= 0.001
Convergence RMSE= 0.0001
Grain Fractions Max Abs Error= 0.001
Max Subgrid Regions= 1
Max Subgrid Length Scale= 3.402823E+38
Initial Layer Thickness= 3.402823E+38
Min Layer Thickness= 3.402823E+38
Max Layer Thickness= 3.402823E+38
Number of Layers= 5

--- SANTEERN.f01 (steady flow) ---

Flow Title=Flows
Program Version=6.31
Number of Profiles= 1
Profile Names=F01pct
River Rch & RM=River 1,Reach 1         ,1935
     482
River Rch & RM=SANTEERN,Main            ,1935
     482
Boundary for River Rch & Prof#=SANTEERN,Main            , 1
Up Type= 0
Dn Type= 3
Dn Slope=0.01889
DSS Import GetInterval= 0
DSS Import GetPeak= 0
DSS Import FillOption= 0

--- SANTEERN.g01 (geometry) ---

Geom Title=Geometry
Program Version=6.31

River Reach=SANTEERN        ,Main
Reach XY= 30
1709638.01198063429802.3234893131709604.18898483429850.522500449
1709531.01592585429893.2127221981709280.80243819429926.732368889
1709242.23806751429975.2949724671709218.04430681429985.778935436
1709168.85032672429956.7464225981709150.30177686429958.359339978
1709071.26882524429982.5531006761708966.42919555429999.488733165
1708895.46083083430030.1341633831708804.33099887430125.296288796
1708734.97555153430164.8127646041708708.36241477 430217.23257945
1708667.23302158430239.8134227681708655.50300797430255.320561215
1708660.78135206430278.5234398861708648.90937812430312.018751601
1708631.33738441430327.876404469 1708600.4792491430330.019330532
1708558.90648347430373.3064370091708570.47828421430399.878720193
1708489.43388067430436.1103066531708417.50409266430444.942545513
1708378.90710429430529.5877398631708317.68226761430580.747980387
 1708237.8090919430622.4772646881708228.40255774430639.526607852
1708246.62771767430737.119399757 1708237.3209258430768.367435724

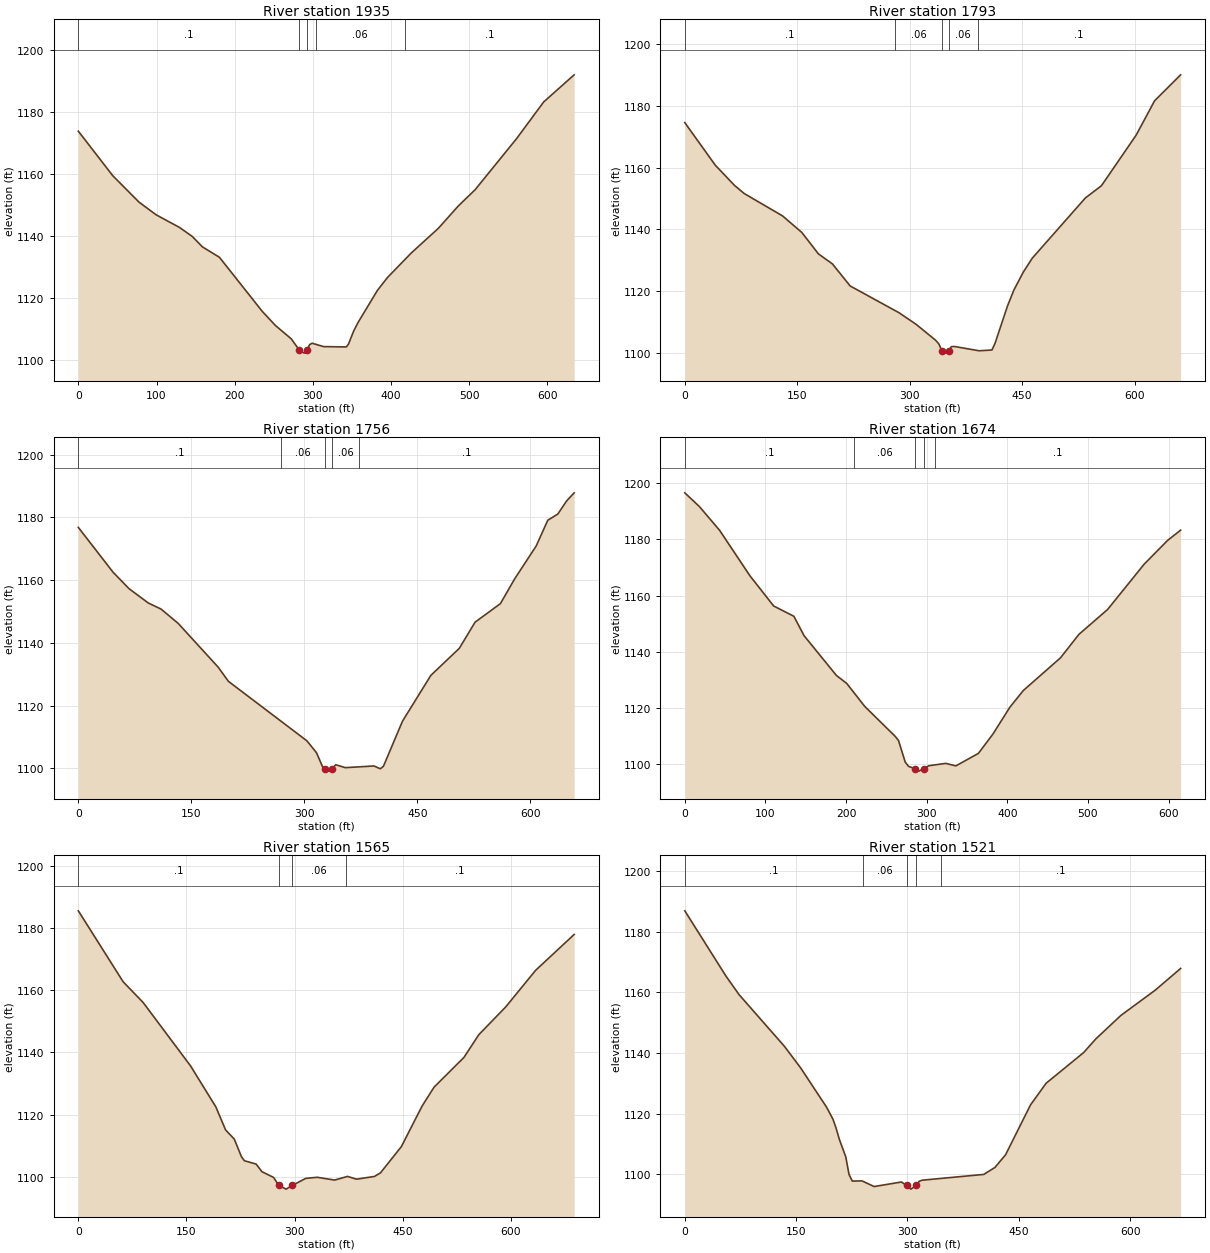
Type RM Length L Ch R = 1 ,1935    ,136.3,141.4,145.3
XS GIS Cut Line= 4
1709501.62536351429571.2237435311709579.04539775429780.903002916
 1709662.9171015 429872.032834881709774.20840071430136.551285182
#Sta/Elev= 30
       0 1173.89      44  1159.5    77.7 1150.92    99.5 1146.84   129.3 1142.76
   145.8 1139.82   158.7 1136.47   180.5 1133.09   235.3 1115.59   252.3 1110.98
   272.3 1106.73   282.8 1103.04   289.1 1102.08  292.31 1103.04     296 1104.86
   299.1 1105.28   313.7 1104.19   342.9 1104.08   345.7 1105.06   352.3 1109.26
   357.8 1111.97   382.6 1122.38   395.6 1126.57     426  1134.5   460.7 1142.49
   486.1  1149.7   507.5 1154.92   560.6 1171.46   595.3 1183.34   634.3 1192.12
#Mann= 5 ,-1,0
       0      .1       0   282.8    .045       0  292.31      .1       0
  303.52     .06       0  417.37      .1       0
Bank Sta=282.8,292.31
XS Rating Curve= 0 ,0
Exp/Cntr(USF)=0,0
Exp/Cntr=0.3,0.1

Type RM Length L Ch R = 1 ,1793    ,37.1,37.8,38
XS GIS Cut Line= 5
1709484.68973102 429578.481871741709562.10976526429784.935296366
1709513.72224386 429863.968247981709491.94785923429938.162447455
1709568.56143478430197.842145617
#Sta/Elev= 30
       0 1174.56    40.6 1160.81    66.3 1154.24    79.1 1151.64   130.4 1144.37
     156 1139.04   178.2 1132.09   196.9 1128.84   220.5 1121.71   285.7 1113.04
   308.6 1109.27   334.6 1104.11   338.8 1102.94   342.9  1100.7   347.1 1099.97
  351.66  1100.7   355.4 1102.06   359.6 1102.12   392.5 1100.73   409.6 1100.98
   413.8 1103.19   430.5 1115.34   438.8 1120.35   451.3 1126.15   463.4  1130.7
   534.2 1150.19   555.6 1154.14   601.9 1170.51   626.5 1181.63   661.2 1190.03
#Mann= 5 ,-1,0
       0      .1       0  280.49     .06       0   342.9    .045       0
  351.66     .06       0  390.48      .1       0
Bank Sta=342.9,351.66
XS Rating Curve= 0 ,0
Exp/Cntr(USF)=0,0
Exp/Cntr=0.3,0.1

Type RM Length L Ch R = 1 ,1756    ,85.4,81.9,79.4
XS GIS Cut Line= 5
1709458.88305295 429588.965834711709525.01266552429776.870709467
1709483.88327233429847.8390741821709452.43138343429934.130154006
1709537.91600456430205.906732517
#Sta/Elev= 30
       0 1176.84    46.2 1162.52    67.4 1157.28    92.8 1152.75   109.8  1150.8
   132.4 1146.27   185.7 1132.25   199.2 1127.76   303.3 1108.81     316 1105.03
   324.5 1100.33  326.73 1099.83   333.1 1099.14   336.4 1099.84   341.6 1101.17
   354.3 1100.25   392.4 1100.78   400.8 1099.89   404.9 1100.69   430.1 1115.02
   467.8 1129.66   505.6 1138.29   526.5 1146.62   560.1 1152.53   579.1 1160.45
   607.6  1170.9     623 1179.12   636.3 1181.09   648.2 1185.34     658 1187.86
#Mann= 5 ,-1,0
       0      .1       0   269.2     .06       0  326.73    .045       0
   336.4     .06       0  373.07      .1       0
Bank Sta=326.73,336.4
XS Rating Curve= 0 ,0
Exp/Cntr(USF)=0,0
Exp/Cntr=0.3,0.1

Type RM Length L Ch R = 1 ,1674    ,117,108.2,100.4
XS GIS Cut Line= 3
1709302.37479685429639.1668905281709452.48110439 430127.30796331
1709479.11091233430228.182970892
#Sta/Elev= 30
       0 1196.58    18.2 1191.67    43.3  1183.2    80.9 1167.03   110.2 1156.33
   135.3 1152.67   147.9 1145.79   188.1 1131.61   200.9 1128.77   223.2 1120.61
   260.9 1109.98   265.1 1108.46   273.4 1100.82   277.6 1099.27  285.22 1098.51
   290.2 1097.59   296.9 1098.51   302.7 1099.51   323.7 1100.35   336.2 1099.45
   364.2  1103.9   382.3 1110.82   403.2 1120.32   419.9 1126.27     466 1137.89
   488.9 1146.25   524.4 1155.08   569.9 1171.24   598.8 1179.64     615  1183.3
#Mann= 5 ,-1,0
       0      .1       0     210     .06       0  285.22    .045       0
   296.9     .06       0     310      .1       0
Bank Sta=285.22,296.9
XS Rating Curve= 0 ,0
Exp/Cntr(USF)=0,0
Exp/Cntr=0.3,0.1

Type RM Length L Ch R = 1 ,1565    ,43.9,44.3,46.1
XS GIS Cut Line= 5
1709123.83395583429714.5728011651709214.43610495429915.689659645
1709293.09071792429929.6284518171709353.82402666429932.615335854
1709438.45240771430248.229415745
#Sta/Elev= 30
       0 1185.66    62.2 1162.79    89.9 1156.12   155.7 1135.68   190.8 1122.48
   204.3 1115.05   216.4 1112.08   226.3 1106.44   230.4 1105.11   246.7 1104.04
   254.8 1101.58     271 1099.72     278 1097.16   288.3 1095.96  296.981097.156
   315.5 1099.42   331.5 1099.78   355.6 1098.88   373.6 1100.06     386 1099.16
   410.9 1100.05   419.2 1101.19   448.2 1109.65   477.1 1122.77   493.7 1128.85
   535.1 1138.42   555.7 1145.74   593.1  1154.7   634.5 1166.48     688 1178.04
#Mann= 4 ,-1,0
       0      .1       0     278    .045       0  296.98     .06       0
  371.27      .1       0
Bank Sta=278,296.98
XS Rating Curve= 0 ,0
Exp/Cntr(USF)=0,0
Exp/Cntr=0.3,0.1

Type RM Length L Ch R = 1 ,1521    ,391.4,399.1,403
XS GIS Cut Line= 4
1709097.94762751429721.5421972511709199.50168476429955.514780136
1709310.01639412429965.4710602591709401.61417125430253.207555807
#Sta/Elev= 30
       0 1186.91    55.6 1165.34      73 1159.31   134.1 1142.27     156 1135.15
   190.8 1122.24   199.5 1118.26   203.8 1115.29   208.2 1111.56   216.8 1105.85
   221.3 1099.95   225.7 1097.79   238.7 1097.86   255.1 1095.99   291.8 1097.49
   298.7 1096.42   304.5 1095.14     312 1096.36   315.9 1097.74   319.9 1098.09
   402.8 1099.99   417.9  1102.3   432.2 1106.48   465.8 1122.93   486.8 1130.05
   537.2 1140.14   553.9 1144.71   587.5 1152.41   633.7 1160.73     668 1167.91
#Mann= 5 ,-1,0
       0      .1       0     240     .06       0   298.7    .045       0
     312     .06       0  345.06      .1       0
Bank Sta=298.7,312
XS Rating Curve= 0 ,0
Exp/Cntr(USF)=0,0
Exp/Cntr=0.3,0.1

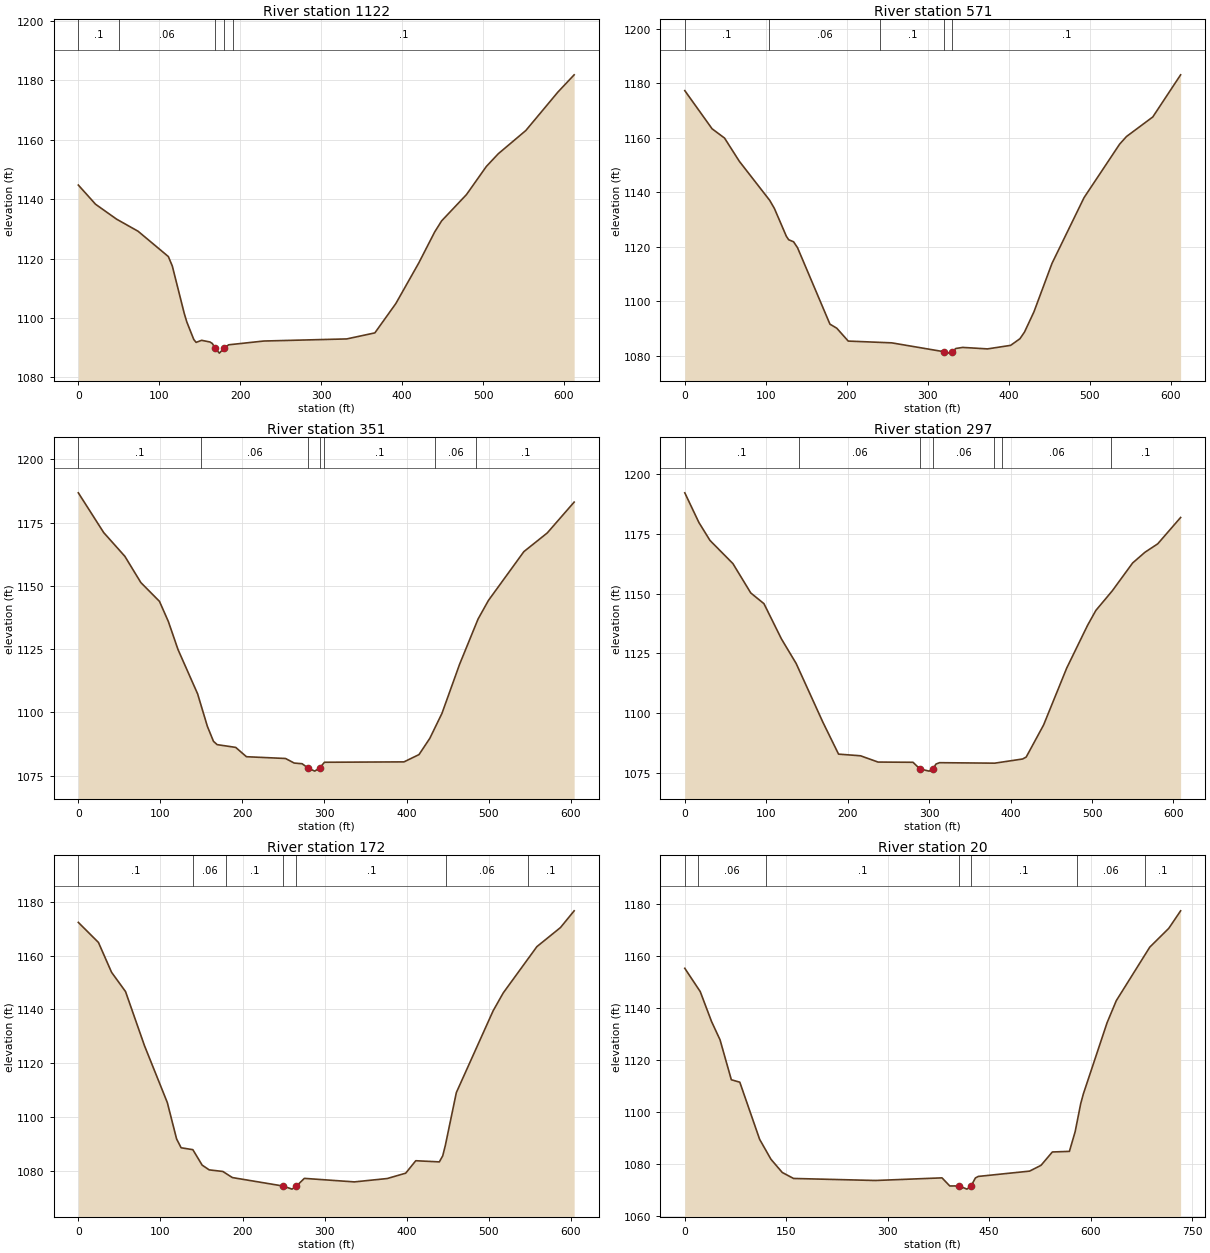
Type RM Length L Ch R = 1 ,1122    ,545.5,550.9,545.9
XS GIS Cut Line= 6
  1708783.729938429893.9974653421708838.12024917429970.356564596
1708888.88491142430041.6251228451708990.41357976430184.162895501
1709084.69062218430316.5186019241709139.08093335430392.878029257
#Sta/Elev= 30
       0 1144.75    21.3 1138.29    47.3 1133.27    73.8 1129.21   111.2 1120.69
   116.1  1117.5   130.8  1101.6     134 1098.69   142.6 1092.79   145.5 1091.81
   152.3  1092.5   162.7 1091.93   165.6 1091.41  168.971089.822   174.2 1088.19
   179.9 1089.81   185.7 1090.99     229 1092.26   331.6 1092.97   366.3    1095
   392.2 1104.87   420.6 1118.56   440.2 1128.96   448.8  1132.7   479.5 1141.55
     504    1151   518.7 1155.27   552.8 1163.11   592.4 1176.04   612.5 1181.85
#Mann= 5 ,-1,0
       0      .1       0      50     .06       0  168.97    .045       0
   179.9     .06       0  191.25      .1       0
Bank Sta=168.97,179.9
XS Rating Curve= 0 ,0
Exp/Cntr(USF)=0,0
Exp/Cntr=0.3,0.1

Type RM Length L Ch R = 1 ,571     ,217.6,220,217.8
BEGIN DESCRIPTION:
Structure 1 XS 4
END DESCRIPTION:
XS GIS Cut Line= 6
1708327.98825465430179.2020558081708395.03897357430244.724890631
 1708511.2605259430358.2978262121708582.78170831430428.188762557
1708699.00293256430541.7620262171708766.05430764430607.284204882
#Sta/Elev= 30
       0 1177.22    33.7 1163.23    49.1 1159.82    67.3 1151.33   104.9 1136.97
   110.7 1133.99   125.5 1123.77   128.3 1122.53   134.4 1121.77   139.3 1119.58
   179.3 1091.56   187.7 1090.08   201.9 1085.35   255.6  1084.7   320.7 1081.42
   326.3 1080.93  330.491081.475   334.8 1082.63   343.3 1083.03   373.9 1082.48
   402.5 1083.78     414 1086.21   419.7 1088.69   431.3 1096.07   453.6 1113.85
   493.2 1137.97   537.1 1157.57   545.6 1160.38   578.1 1167.56   612.5 1183.02
#Mann= 5 ,-1,0
       0      .1       0  103.75     .06       0  241.25      .1       0
   320.7    .045       0  330.49      .1       0
Bank Sta=320.7,330.49
XS Rating Curve= 0 ,0
Exp/Cntr(USF)=0,0
Exp/Cntr=0.3,0.1

Type RM Length L Ch R = 1 ,351     ,53,53.6,53.3
BEGIN DESCRIPTION:
Structure 1 XS 3
END DESCRIPTION:
XS GIS Cut Line= 5
1708198.38812056430290.5848949611708421.77717768430536.554795394
1708441.93864493430579.2971059611708445.97093838430614.781288319
1708591.93996126 430734.94363312
#Sta/Elev= 30
       0 1186.74    30.9 1171.05    56.7 1161.68    76.2 1151.31    98.9 1143.88
   109.7 1135.95   121.5 1124.85   145.4 1107.35   157.3 1094.51   164.7 1088.63
   169.2 1087.31   191.8 1086.22   204.9 1082.54   252.5 1081.84   263.1 1080.04
   272.8 1079.77   280.1 1078.04   288.1 1076.85   294.1 1078.09     300 1080.35
   396.9  1080.5   415.2 1083.38   428.4 1089.81   443.2 1099.67   464.6 1118.98
   487.2 1136.91   499.8 1144.23     543 1163.52   571.5 1170.89   604.3 1183.08
#Mann= 7 ,-1,0
       0      .1       0     150     .06       0   280.1    .045       0
   294.1     .06       0     300      .1       0  435.24     .06       0
  485.24      .1       0
Bank Sta=280.1,294.1
XS Rating Curve= 0 ,0
Exp/Cntr(USF)=0,0
Exp/Cntr=0.3,0.1

Type RM Length L Ch R = 1 ,297     ,125,125.2,124.3
BEGIN DESCRIPTION:
Structure 1 XS 2
END DESCRIPTION:
XS GIS Cut Line= 4
1708160.48456214430324.4561599391708395.16404091430584.135858101
1708399.19633436430626.8781686681708570.97203532430757.524476439
#Sta/Elev= 30
       0  1192.3    17.3 1179.87    30.9 1172.35    59.1 1162.61      81 1150.31
    97.2 1145.81   118.7    1131   136.7 1120.75   169.7 1095.99   188.8 1082.71
   215.8 1082.01   237.3 1079.38   280.2 1079.29   288.7 1076.49     300 1075.58
  304.411076.521   308.5 1078.56   312.8 1079.12   380.6 1078.92   414.8 1080.67
   419.2 1081.49   440.5  1094.9     469 1118.85   494.6 1136.77   504.7 1142.96
   524.8 1151.16   549.9 1162.89     565 1167.37   580.7 1170.91   608.8 1181.96
#Mann= 7 ,-1,0
       0      .1       0     140     .06       0   288.7    .045       0
  304.41     .06       0  380.01      .1       0  390.01     .06       0
  522.94      .1       0
Bank Sta=288.7,304.41
XS Rating Curve= 0 ,0
Exp/Cntr(USF)=0,0
Exp/Cntr=0.3,0.1

Type RM Length L Ch R = 1 ,172     ,154.8,152.4,148.5
BEGIN DESCRIPTION:
Structure 1 XS 1
END DESCRIPTION:
XS GIS Cut Line= 3
1708076.28738088430431.0974523111708355.47651586430714.833641606
1708556.45631661430759.394773899
#Sta/Elev= 30
       0 1172.36    24.5  1164.9    40.5 1153.79    57.5 1146.63    80.6 1126.49
   108.4 1105.34   119.7 1091.81   125.2 1088.54   139.5 1087.83   150.8 1082.09
   159.4 1080.32     176 1079.73   187.6 1077.46   249.8 1074.29   260.2 1073.16
   265.71074.314   275.3 1077.16   336.2 1075.85   376.2  1077.1   398.7 1079.09
     411 1083.72   439.7 1083.29   443.8 1085.53     447 1089.41   460.4 1109.06
   505.2 1139.47   517.5 1146.12   558.5 1163.34   587.2 1170.43   603.9 1176.66
#Mann= 7 ,-1,0
       0      .1       0     140     .06       0     180      .1       0
   249.8    .045       0   265.7      .1       0  448.06     .06       0
  548.06      .1       0
Bank Sta=249.8,265.7
XS Rating Curve= 0 ,0
Exp/Cntr(USF)=0,0
Exp/Cntr=0.3,0.1

Type RM Length L Ch R = 1 ,20      ,,,
XS GIS Cut Line= 4
1707964.51510048430510.7481173161708014.51553926430674.459231374
1708403.22862781430801.8797043861708554.03640283430778.492402377
#Sta/Elev= 30
       0 1155.12    22.8 1146.18    39.5  1134.7    52.1 1127.63    68.8 1112.28
    81.3 1111.35   110.6  1089.4   127.3 1081.74   144.1 1076.63   160.8 1074.34
   281.9 1073.56   380.2 1074.57   391.7 1071.45   405.5 1071.48     417 1070.24
  423.191071.482   429.6 1074.54   433.8 1075.12   509.6 1077.16   526.5 1079.38
   543.3 1084.52   568.5 1084.75     577 1092.32   585.2 1103.08   589.2 1106.91
   624.2 1134.22   637.8 1142.68   687.3 1163.26   715.4 1170.49   732.9 1177.22
#Mann= 7 ,-1,0
       0      .1       0      20     .06       0     120      .1       0
   405.5    .045       0  423.19      .1       0  580.24     .06       0
  680.24      .1       0
Bank Sta=405.5,423.19
XS Rating Curve= 0 ,0
Exp/Cntr(USF)=0,0
Exp/Cntr=0.3,0.1
LCMann Table=0

Chan Stop Cuts=-1
Use User Specified Reach Order=0
Composite Channel Slope=5